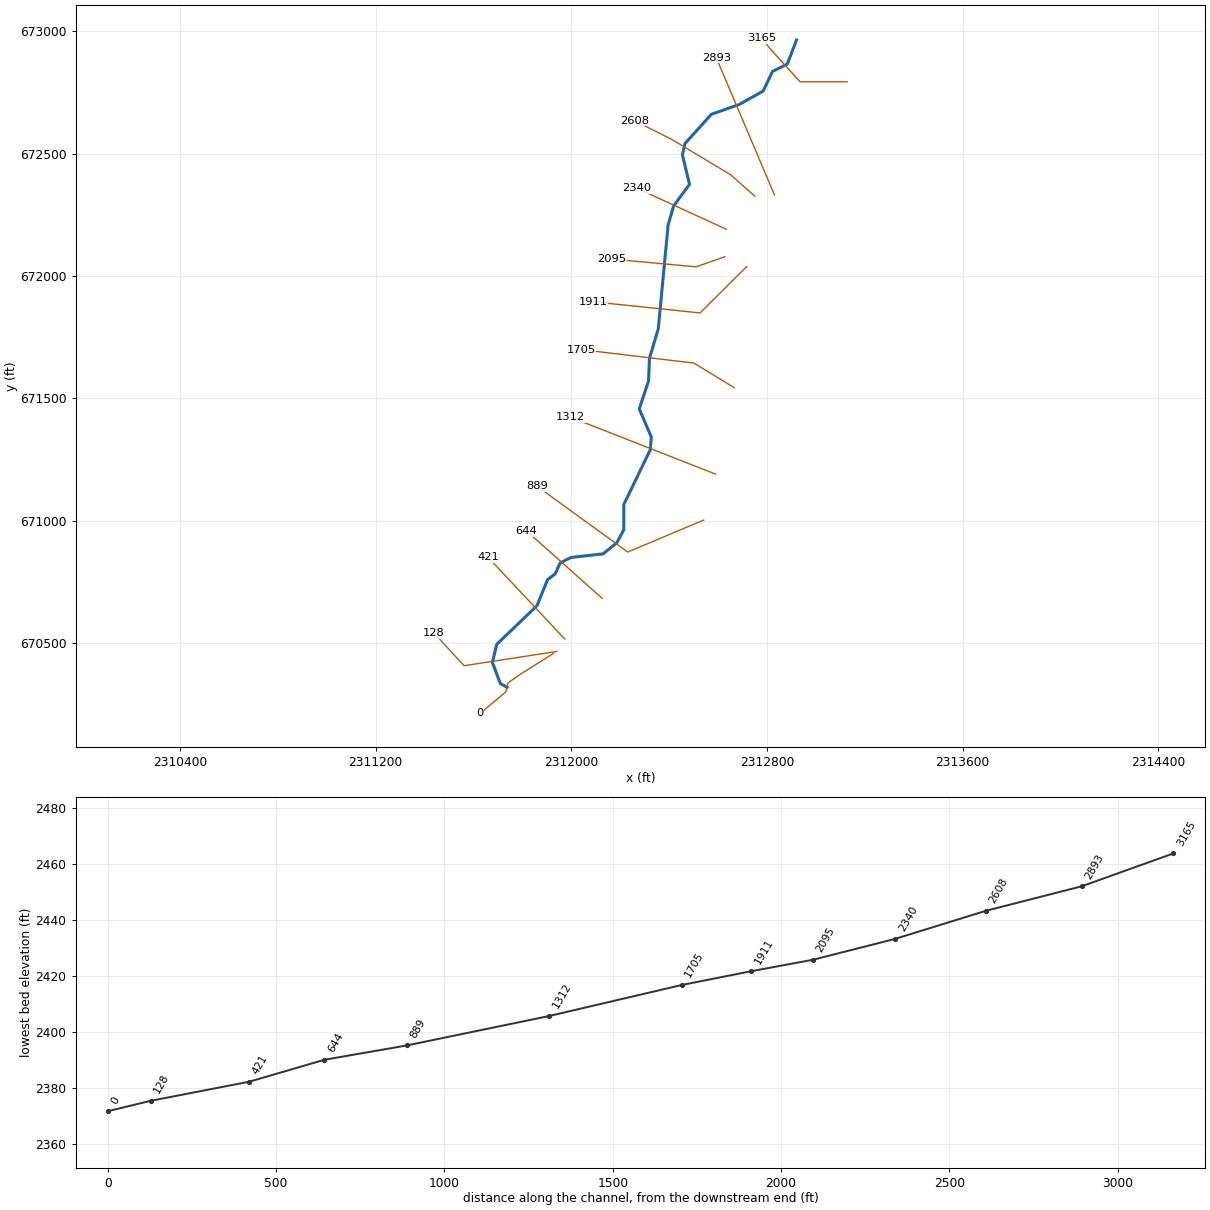
--- FILESRN.prj (project) ---

Proj Title=FILESRN
Current Plan=p01
Default Exp/Contr=0,0
English Units
Geom File=g01
Flow File=f01
Plan File=p01
BEGIN DESCRIPTION:
----------MODEL BY WOOD PLC 2022----------
AFH study
Randolph County, WV
HEC-RAS Version: RAS 6.2
Vertical Datum: NAVD88
Projection: NAD 1983 StatePlane West Virginia S FIPS 4702 (US Feet)
Terrain: 1-meter LIDAR (FEMA Region III 3DEP collected 2016-2018)
Land Use: 2019 NLCD
Hydrologic Method:
WV SIR2010-5033 regression equations
Additional Model Notes:
Main stem name change DS; KWSEL tie-in
END DESCRIPTION:
DSS Export Rating Curves= 0
DSS Export Rating Curve Sorted= 0
DSS Export Volume Flow Curves= 0
DXF OffsetX= 0
DXF OffsetY= 0
DXF ScaleX= 0
DXF ScaleY= 0

--- FILESRN.p01 (plan) ---

Plan Title=Floodplain
Program Version=6.20
Short Identifier=Floodplain
Geom File=g01
Flow File=f01
Subcritical Flow
K Sum by GR= 0
Std Step Tol= 0.01
Critical Tol= 0.01
Num of Std Step Trials= 20
Max Error Tol= 0.3
Flow Tol Ratio= 0.001
Split Flow NTrial= 30
Split Flow Tol= 0.02
Split Flow Ratio= 0.02
Log Output Level= 0
Friction Slope Method= 1
Unsteady Friction Slope Method= 2
Unsteady Bridges Friction Slope Method= 1
Parabolic Critical Depth
Global Vel Dist= 0 , 0 , 0
Global Log Level= 0
CheckData=True
Encroach Param=-1 ,0,0, 0
Mapping Interval=1HOUR
Computation Time Step Use Courant=        0
Computation Time Step Use Time Series=    0
Computation Time Step Count To Double=0
Computation Time Step Max Doubling=0
Computation Time Step Max Halving=0
Computation Time Step Residence Courant=0
Run HTab= 0
Run UNet= 0
Run Sediment= 0
Run PostProcess= 0
Run WQNet= 0
Run RASMapper=-1
UNET Theta= 0
UNET Theta Warmup= 0
UNET ZTol= 0
UNET ZSATol= 0
UNET MxIter= 0
UNET Max Iter WO Improvement= 0
UNET MaxInSteps= 0
UNET DtIC= 0
UNET DtMin= 0
UNET MaxCRTS= 0
UNET WFStab= 0
UNET SFStab= 0
UNET WFX= 1
UNET SFX= 1
UNET Gravity=32.174
UNET 1D Methodology=Finite Difference
UNET DSS MLevel= 1
UNET Pardiso=0
UNET DZMax Abort= 0
UNET Use Existing IB Tables= 0
UNET Froude Reduction=False
UNET Froude Limit= 0
UNET Froude Power= 0
UNET D1 Cores= 0
UNET WindReference=Eulerian
UNET WindDragFormulation=Hsu (1988)
UNET D2 Coriolis=0
UNET D2 Cores= 0
UNET D2 Theta= 1
UNET D2 Theta Warmup= 1
UNET D2 Z Tol= 0.01
UNET D2 Volume Tol= 0.01
UNET D2 Max Iterations= 20
UNET D2 Equation= 0
UNET D2 RampUpFraction=0.1
UNET D2 TimeSlices= 1
UNET D2 Turbulence Formulation=Non-Conservative (original)
UNET D2 Eddy Viscosity=0.3
UNET D2 Transverse Eddy Viscosity=0.1
UNET D2 Smagorinsky Mixing=0
UNET D2 BCVolumeCheck=0
UNET D2 Cores=0
UNET D2 SolverType=PARDISO (Direct)
UNET D2 Minimum Iterations= 2147483647
UNET D2 Maximum Iterations= 2147483647
UNET D2 Restart Number= 10
UNET D2 Relaxation Coeff=1.3
UNET D2 SOR Precondition Iterations= 10
UNET D2 ILUT Maximum Fill= 8
UNET D2 ILUT Tolerance=1E-08
UNET D1D2 MaxIter= 0
UNET D1D2 ZTol=0.01
UNET D1D2 QTol=0.1
UNET D1D2 MinQTol=1
Write IC File= 0
Write IC File at Fixed DateTime=0
Write IC File at Sim End=0
Echo Input=False
Echo Parameters=False
Echo Output=False
Write Detailed= 0
HDF Write Warmup=0
HDF Write Time Slices=0
HDF Flush=0
HDF Compression= 1
HDF Chunk Size= 1
HDF Spatial Parts= 1
HDF Use Max Rows=0
HDF Fixed Rows= 1
Calibration Method= 0
Calibration Iterations= 20
Calibration Max Change=0.05
Calibration Tolerance=0.2
Calibration Maximum=1.5
Calibration Minimum=0.5
Calibration Optimization Method= 1
WQ AD Non Conservative
WQ ULTIMATE=-1
WQ Max Comp Step=1HOUR
WQ Output Interval=15MIN
WQ Output Selected Increments= 0
WQ Output face flow=0
WQ Output face velocity=0
WQ Output face area=0
WQ Output face dispersion=0
WQ Output cell volume=0
WQ Output cell surface area=0
WQ Output cell continuity=0
WQ Output cumulative cell continuity=0
WQ Output face conc=0
WQ Output face dconc_dx=0
WQ Output face courant=0
WQ Output face peclet=0
WQ Output face adv mass=0
WQ Output face disp mass=0
WQ Output cell mass=0
WQ Output cell source sink temp=0
WQ Output nsm pathways=0
WQ Output nsm derived pathways=0
WQ Create Restart=0
WQ Fixed Restart=0
WQ System Summary=0
WQ Write To DSS=0
Sorting and Armoring Iterations= 10
XS Update Threshold= 0.02
Bed Roughness Predictor= 0
Hydraulics Update Threshold= 0.02
Energy Slope Method= 1
Volume Change Method= 1
Sediment Retention Method= 0
Sediment TS Multiplier= 1
Warm Up Method= 0
XS Weighting Method= 0
Number of US Weighted Cross Sections= 1
Number of DS Weighted Cross Sections= 1
Upstream XS Weight=0
Main XS Weight=1
Downstream XS Weight=0
Number of DS XS's Weighted with US Boundary= 1
Upstream Boundary Weight= 1
Weight of XSs Associated with US Boundary= 0
Number of US XS's Weighted with DS Boundary= 1
Downstream Boundary Weight= 0.5
Weight of XSs Associated with DS Boundary= 0.5
Percentile Method= 0
Sediment Output Level= 3
Mass or Volume Output= 0
Output Increment Type= 1
Profile and TS Output Increment= 1
Transport Output Increment 1
XS Output Flag= 0
XS Output Increment= 10
Read HDF5 Sediment Hotstart= 0
Sediment Hotstart Type= 0
Write Gradation File= 0
Read Gradation Hotstart= 0
Write HDF5 File= 1
Write Binary Output= 1
Write DSS Sediment File= 0
DSS Sediment Output Type= 1
SV Curve= 0
Specific Gage Flag= 0
Subcell Erosion Methods= 0
Subcell Deposition Methods= 0
Advection Scheme= 1
Matrix Solver= 0
Implicit Weighting Factor= 1
Maximum Outer Loop Convergence Iterations= 5
Convergence Maximum Absolute= 0.001
Convergence RMSE= 0.0001
Grain Fractions Max Abs Error= 0.001
Max Subgrid Regions= 1
Max Subgrid Length Scale= 3.402823E+38
Initial Layer Thickness= 3.402823E+38
Min Layer Thickness= 3.402823E+38
Max Layer Thickness= 3.402823E+38
Number of Layers= 5

--- FILESRN.f01 (steady flow) ---

Flow Title=Flow
Program Version=6.20
Number of Profiles= 1
Profile Names=P100yr
River Rch & RM=FILESRN,Main            ,3165
     476
River Rch & RM=FILESRN,Main            ,128
     647
River Rch & RM=FILESRN,Main            ,0
     857
Boundary for River Rch & Prof#=FILESRN,Main            , 1
Up Type= 0
Dn Type= 1
Dn Known WS=2375.3
DSS Import GetInterval= 0
DSS Import GetPeak= 0
DSS Import FillOption= 0

--- FILESRN.g01 (geometry) ---

Geom Title=Geometry
Program Version=6.20

River Reach=FILESRN         ,Main
Reach XY= 30
 2312920.8644916672964.902285174 2312883.0187248672865.963438615
2312822.66679068672836.336125493 2312784.3051544672755.956614912
2312685.02500001672700.3570000082312572.89200002672661.064999998
     2312464.296672540.9159999942312454.22700001672494.815000013
2312483.20600003672374.7090000212312418.26500005672286.030000001
2312395.83200002672209.0810000152312355.55400003      671784.081
2312319.39205165671662.7896413362312315.97100003671571.581000015
2312277.77699998671456.3030000032312327.08200003671341.720000014
2312322.91499999671289.6369999952312214.58200002      671065.331
2312214.58200002670962.5530000182312186.11000003      670909.081
2312129.80500002670863.888999999 2311998.4478569670849.113464013
2311954.64764281670826.974121541 2311933.4928811670781.372005314
  2311902.828612670758.4404649442311859.31733184670651.391194075
     2311695.242670494.2319999932311677.39513411670420.308969244
     2311709.825670333.815000013  2311737.099898670318.610785305

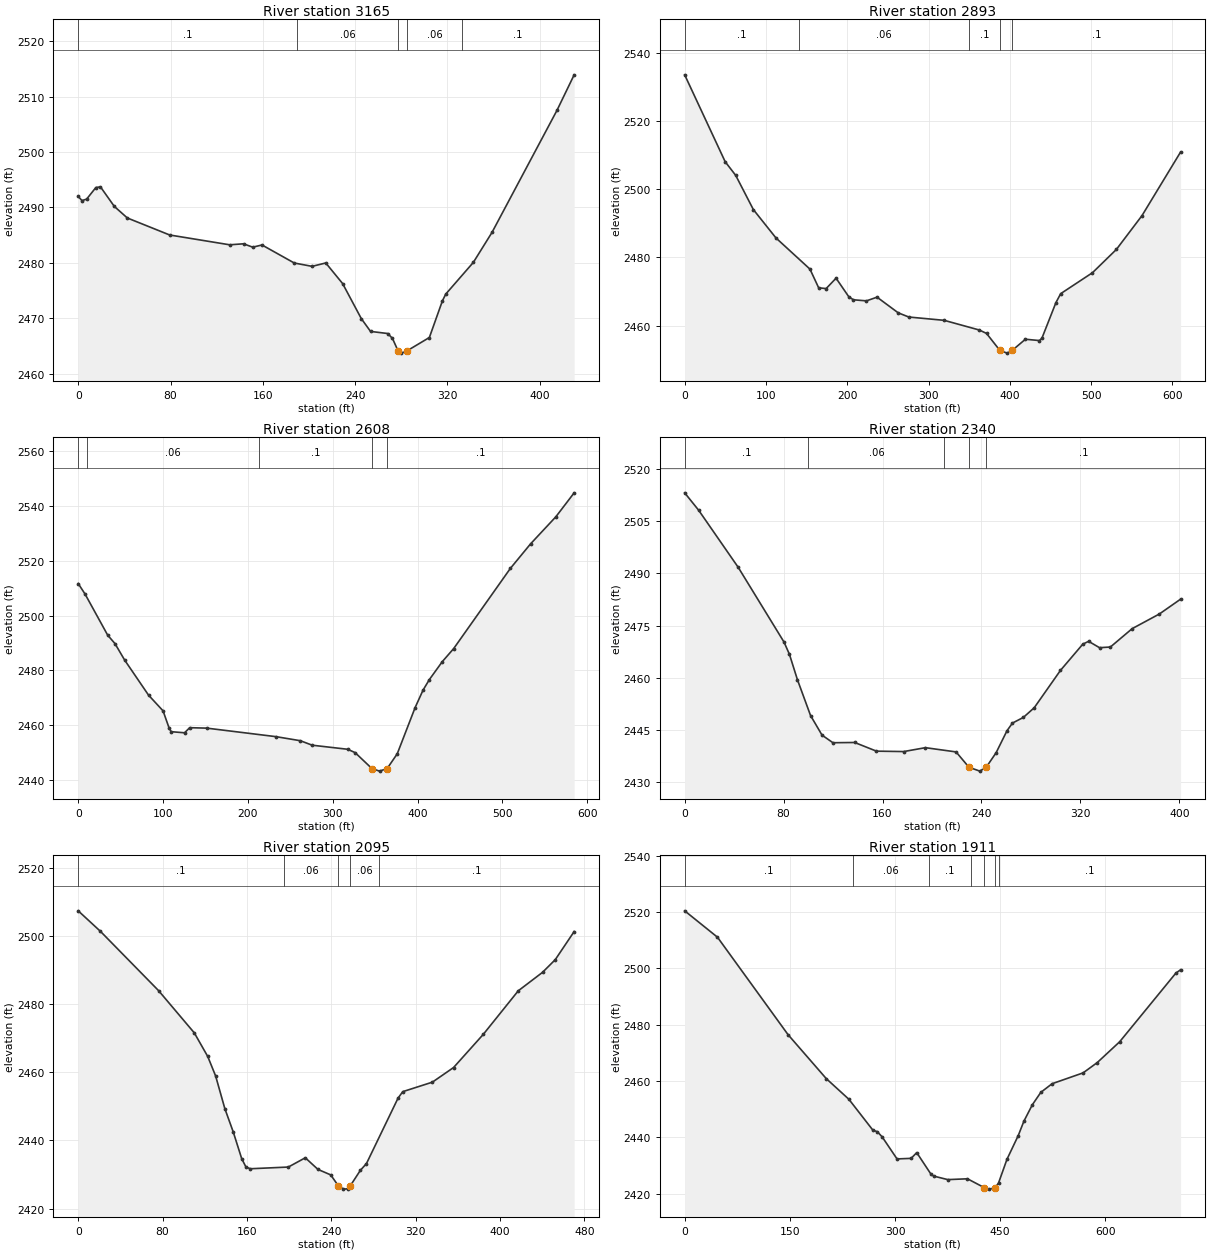
Type RM Length L Ch R = 1 ,3165    ,274.9,272.4,269.7
XS GIS Cut Line= 4
2313127.45711093672793.8183258072312935.05489327672793.857415217
2312818.05078438672923.250194465  2312777.443476672971.428356952
#Sta/Elev= 30
       0 2491.97     3.3 2491.22     7.3 2491.49    15.3 2493.58    19.3  2493.7
    31.3 2490.17    42.6 2488.08    79.3 2485.01   131.3 2483.24   143.3 2483.42
   151.3 2482.81   159.3 2483.21   187.3 2479.95   202.7 2479.35   214.6 2479.96
   229.2 2476.24   245.4 2469.91   253.4  2467.6   268.3 2467.22   272.4 2466.34
277.22712464.105   280.2 2463.68285.38712464.138   304.4  2466.5   315.7 2473.12
   318.6 2474.34   342.5 2480.06   358.7 2485.48     415 2507.51   429.9 2513.93
#Mann= 5, -1 ,  0
       0     0.1       0     190    0.06       0277.2271   0.045       0
285.3871    0.06       0   332.4     0.1       0
Bank Sta=277.2271,285.3871
XS Rating Curve= 0 ,0
Exp/Cntr(USF)=0,0
Exp/Cntr=0.3,0.1

Type RM Length L Ch R = 1 ,2893    ,278.6,285,289.2
XS GIS Cut Line= 2
2312830.43945473672331.3470553492312592.30168016672892.966778046
#Sta/Elev= 30
       0  2533.5    49.8 2508.04    62.8 2504.02    84.5    2494   112.3 2485.69
   154.1 2476.56   164.8 2471.08     174 2470.86   186.2  2473.9   201.8 2468.48
   207.5 2467.57   223.6 2467.26   236.6 2468.34   262.7 2463.74   275.7 2462.52
   319.2 2461.55   362.6  2458.7   371.3 2457.71  387.73 2452.72   396.7 2451.94
   402.8 2452.73   419.1 2456.01   436.4 2455.62   439.4 2456.31   456.6 2466.73
   462.5 2469.37   501.6 2475.51     531 2482.33   562.5 2492.24     610 2510.89
#Mann= 5, -1 ,  0
       0     0.1       0     140    0.06       0     350     0.1       0
  387.73   0.045       0   402.8     0.1       0
Bank Sta=387.73,402.8
XS Rating Curve= 0 ,0
Exp/Cntr(USF)=0,0
Exp/Cntr=0.3,0.1

Type RM Length L Ch R = 1 ,2608    ,264.9,268.3,267.9
XS GIS Cut Line= 4
2312750.20957058672326.0627975822312650.95714377672414.018752655
2312410.54076951672558.3317978292312257.24328966672635.153669817
#Sta/Elev= 30
       0 2511.69     8.1 2507.84    34.8  2492.8    43.3 2489.77    54.7 2483.75
    82.9 2470.92     100 2465.18   107.2 2458.83   109.6 2457.57   125.3 2457.17
   131.4 2459.03   151.5 2458.87   233.2 2455.75   261.8 2454.27   275.8 2452.63
   317.7 2451.14   326.4 2449.91  346.12 2444.11   355.1 2443.16   364.1  2444.1
     376 2449.49   397.1  2466.4   406.4 2472.75   413.9 2476.63   429.1 2483.16
   442.5 2487.93   509.3 2517.22   533.1 2526.18     563 2536.11   584.5 2544.84
#Mann= 5, -1 ,  0
       0     0.1       0      10    0.06       0  212.62     0.1       0
  346.12   0.045       0   364.1     0.1       0
Bank Sta=346.12,364.1
XS Rating Curve= 0 ,0
Exp/Cntr(USF)=0,0
Exp/Cntr=0.3,0.1

Type RM Length L Ch R = 1 ,2340    ,242.7,244.4,247.4
XS GIS Cut Line= 2
2312633.11614361 672191.128258192312268.54189601672358.397408725
#Sta/Elev= 30
       0 2513.15    11.3 2508.15    43.3 2491.74    80.3 2470.29    84.7 2466.77
    91.2 2459.44   101.8 2449.16   111.1 2443.52   119.9 2441.34   137.5 2441.41
   155.1 2438.92   177.1  2438.8   194.7 2439.92   219.5  2438.7   229.9  2434.3
   238.7 2433.18  243.87 2434.29   251.9 2438.48   260.7  2444.8   265.1 2446.99
   273.9 2448.61   282.7 2451.39   303.9 2462.12     322 2469.67   326.7 2470.48
   335.5 2468.65   344.3 2468.84   361.9 2474.12   383.9 2478.33   401.1  2482.6
#Mann= 5, -1 ,  0
       0     0.1       0     100    0.06       0     210     0.1       0
   229.9   0.045       0  243.87     0.1       0
Bank Sta=229.9,243.87
XS Rating Curve= 0 ,0
Exp/Cntr(USF)=0,0
Exp/Cntr=0.3,0.1

Type RM Length L Ch R = 1 ,2095    ,184.3,184.3,184.3
XS GIS Cut Line= 3
2312628.03827926672078.6344478962312510.22924938672037.306572032
2312166.34552891672068.951451299
#Sta/Elev= 30
       0 2507.39    21.1 2501.36    76.2 2483.96   110.1 2471.55   122.8 2464.64
   130.3  2458.9     139 2449.35     147 2442.47     155 2434.65     159 2432.21
   163.1 2431.68   199.2 2432.18   215.3  2434.9   227.3 2431.49   239.4 2429.88
   246.7 2426.63   251.4  2425.7   255.4 2425.79  257.84 2426.62   267.5 2431.21
   273.3 2433.21   303.2 2452.39   307.7 2454.31   335.8  2457.1   355.9  2461.4
     384 2471.11   417.2 2483.91   440.2 2489.33   452.3 2493.06   470.2 2501.31
#Mann= 5, -1 ,  0
       0     0.1       0  194.85    0.06       0   246.7   0.045       0
  257.84    0.06       0  284.85     0.1       0
Bank Sta=246.7,257.84
XS Rating Curve= 0 ,0
Exp/Cntr(USF)=0,0
Exp/Cntr=0.3,0.1

Type RM Length L Ch R = 1 ,1911    ,206.3,206.2,205.7
XS GIS Cut Line= 3
2312716.87664316672038.1485236472312526.22877161671848.877171023
2312089.87227137671894.302295653
#Sta/Elev= 30
       0 2520.46    46.8 2511.08   147.5 2476.45     202 2460.84   234.2 2453.52
   268.6 2442.49   274.7 2442.01   281.7 2440.15   302.9 2432.32     323 2432.52
     331 2434.56   351.1 2426.98   355.2 2426.22   375.3 2424.97   403.4 2425.26
   427.6 2422.09   434.7 2421.59  442.99 2422.09   447.7 2423.78   459.7 2432.18
   475.8 2440.62   483.9 2445.75   495.9 2451.56     508 2455.97   524.1 2459.04
   568.3 2462.89   588.4 2466.53   620.5 2473.95   700.6 2498.33   707.4 2499.52
#Mann= 7, -1 ,  0
       0     0.1       0     240    0.06       0  348.65     0.1       0
  408.65    0.06       0   427.6   0.045       0  442.99    0.06       0
  448.65     0.1       0
Bank Sta=427.6,442.99
XS Rating Curve= 0 ,0
Exp/Cntr(USF)=0,0
Exp/Cntr=0.3,0.1

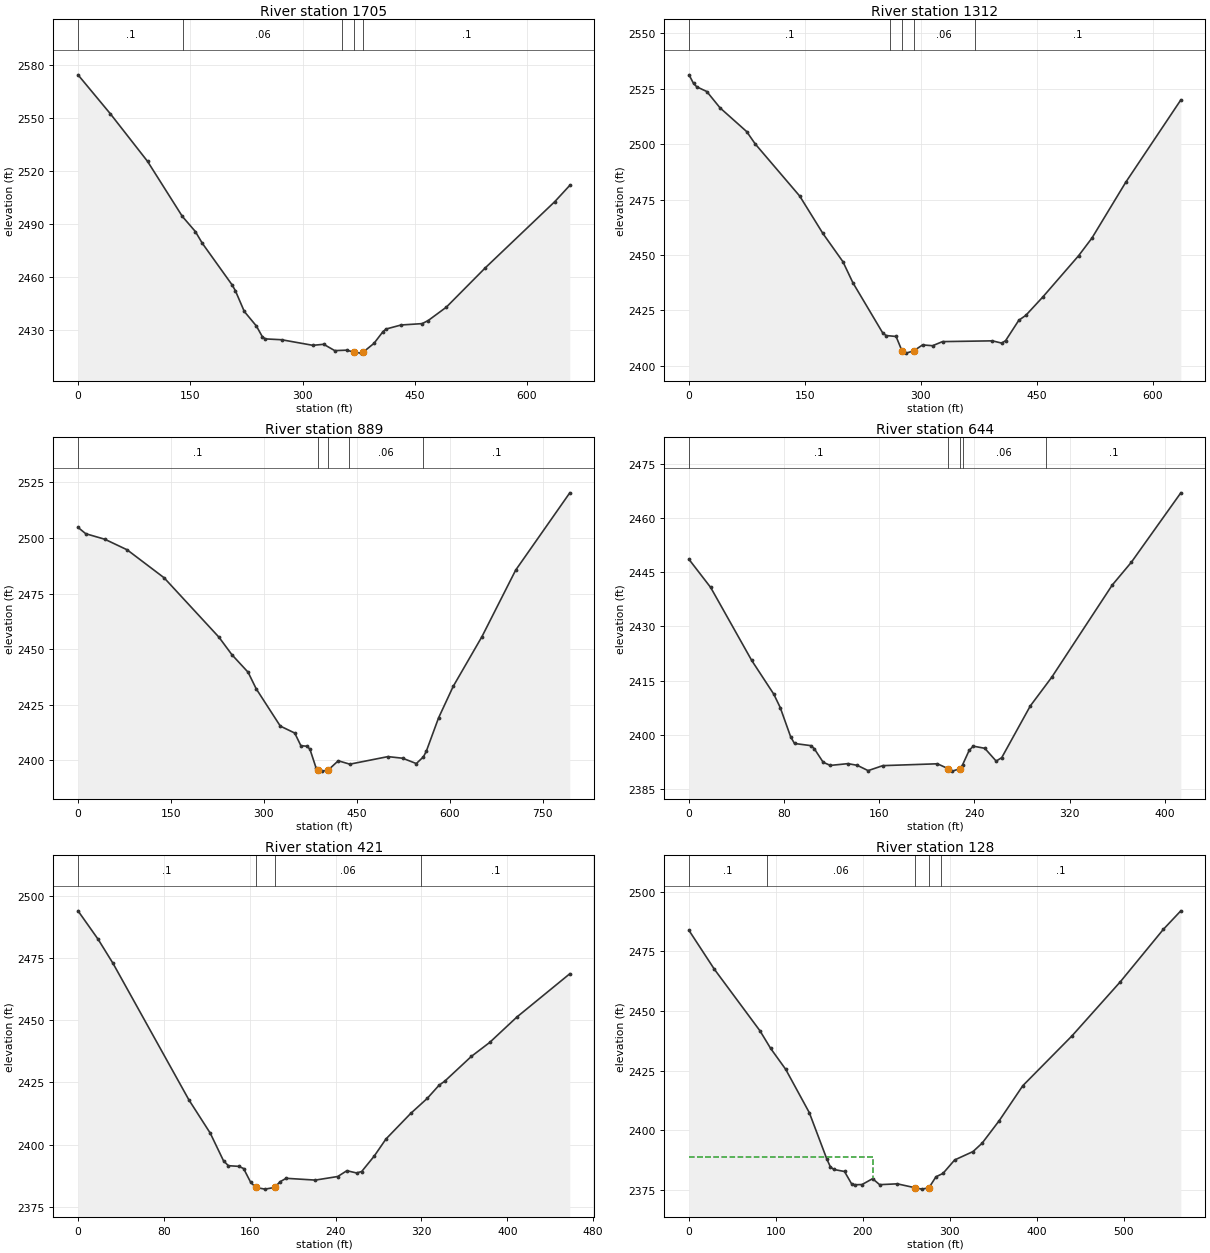
Type RM Length L Ch R = 1 ,1705    ,394.7,392.7,390.7
XS GIS Cut Line= 3
2312665.94544281671543.289968967 2312501.4514309671643.775850724
2312040.31758996671698.836607851
#Sta/Elev= 30
       0 2574.45    43.4 2552.28    92.9 2525.41   139.4  2494.2   156.8 2485.62
   166.1 2478.96     206 2455.31   210.2 2452.16   222.2 2440.31   238.4 2432.03
   246.4 2425.93   250.4 2424.74   272.1 2424.26   313.9 2421.09   328.3 2421.68
   343.1 2418.09   359.2 2418.35  369.292417.132   378.7 2416.67  380.952417.193
   395.5  2422.2   407.5 2428.83   411.6 2430.32   431.7 2432.62   459.9  2433.4
     468 2435.16   492.1 2442.69   544.2 2464.99   637.2 2502.58   657.2 2511.79
#Mann= 5, -1 ,  0
       0     0.1       0     140    0.06       0  352.76     0.1       0
  369.29   0.045       0  380.95     0.1       0
Bank Sta=369.29,380.95
XS Rating Curve= 0 ,0
Exp/Cntr(USF)=0,0
Exp/Cntr=0.3,0.1

Type RM Length L Ch R = 1 ,1312    ,424.9,423.3,420.8
XS GIS Cut Line= 2
2312589.59719018671189.904869229 2311997.0057916671422.536568091
#Sta/Elev= 30
       0 2531.32     5.8 2527.45    10.1 2525.88      23 2523.78    40.2 2516.38
    74.6 2505.69    85.6 2500.14   143.3 2476.55   173.3 2459.66   199.2 2446.92
   212.1 2437.42   250.8  2414.7   255.1 2413.56     268 2413.15  275.69 2406.63
   280.8 2405.62   290.6  2406.6   302.3 2409.33   315.3 2408.97   328.1 2410.82
   392.6 2411.17   404.8 2410.15   409.8 2411.27   426.9 2420.47   435.9 2422.67
   457.8 2430.92   504.3 2449.63   521.5 2457.57   565.2 2482.74   636.6 2519.99
#Mann= 5, -1 ,  0
       0     0.1       0     260    0.06       0  275.69   0.045       0
   290.6    0.06       0     370     0.1       0
Bank Sta=275.69,290.6
XS Rating Curve= 0 ,0
Exp/Cntr(USF)=0,0
Exp/Cntr=0.3,0.1

Type RM Length L Ch R = 1 ,889     ,247.3,244.9,242
XS GIS Cut Line= 3
2312541.29400654671002.0121370982312230.63915545670871.418706847
2311860.68186983671139.664029916
#Sta/Elev= 30
       0 2504.78    12.5 2501.93    43.4 2499.43    79.3 2494.69     139  2482.1
   227.6 2455.35   248.5 2447.47   274.6  2439.6   287.6 2432.19   326.6 2415.36
   349.9 2412.23   359.8 2406.55   369.7 2406.29   374.4 2404.99   384.5 2396.41
387.45912395.637   394.4 2395.09403.94912395.592   420.2 2399.75   438.8 2398.22
   500.4 2401.62     524  2400.9   546.2  2398.5   557.7 2401.53   562.4 2404.09
   582.1 2419.04   605.7  2433.2   652.2 2455.63   706.6 2485.54     794 2520.33
#Mann= 5, -1 ,  0
       0     0.1       0387.4591   0.045       0403.9491     0.1       0
  436.99    0.06       0  556.99     0.1       0
Bank Sta=387.4591,403.9491
XS Rating Curve= 0 ,0
Exp/Cntr(USF)=0,0
Exp/Cntr=0.3,0.1

Type RM Length L Ch R = 1 ,644     ,223.1,223,220.6
XS GIS Cut Line= 2
2312125.77926712670682.1103054172311817.10615993670957.440424065
#Sta/Elev= 30
       0 2448.54    18.2 2440.78    52.7  2420.6    71.3 2411.25    76.7 2407.56
    85.5 2399.44    88.7 2397.62   102.5 2397.02   105.3 2396.19   112.8 2392.43
   118.8 2391.55   133.6 2392.04   141.5 2391.58   150.6 2390.11     163 2391.49
   208.9    2392  217.67 2390.69   221.5 2389.97  228.09 2390.68     230 2391.67
   235.6 2395.72     239 2396.88   248.7 2396.29   258.3 2392.75     263 2393.71
     287    2408   305.1 2415.97   355.9 2441.44     372 2447.76   413.6 2466.96
#Mann= 5, -1 ,  0
       0     0.1       0  217.67   0.045       0  228.09     0.1       0
     230    0.06       0     300     0.1       0
Bank Sta=217.67,228.09
XS Rating Curve= 0 ,0
Exp/Cntr(USF)=0,0
Exp/Cntr=0.3,0.1

Type RM Length L Ch R = 1 ,421     ,284.8,292.5,300.5
XS GIS Cut Line= 2
2311972.96226836670515.8913632872311659.51625728670850.107893173
#Sta/Elev= 30
       0 2493.97    18.7 2482.56    32.6 2472.87   103.3 2418.02   123.2 2404.64
   135.6  2393.5   140.1 2391.56   149.8 2391.29   154.3 2390.41   160.8 2384.93
   165.6 2382.82   174.1 2382.14  183.172382.807   188.2 2385.09   193.9 2386.49
   221.1 2385.77     242 2387.21   250.5 2389.54   259.5 2388.64   264.3 2389.22
     276 2395.43   286.9 2402.27   309.9 2412.53   325.3 2418.57   336.3 2423.84
   341.8 2425.56   366.5 2435.48   383.5 2441.06     409 2451.33   458.2 2468.68
#Mann= 4, -1 ,  0
       0     0.1       0   165.6   0.045       0  183.17    0.06       0
     320     0.1       0
Bank Sta=165.6,183.17
XS Rating Curve= 0 ,0
Exp/Cntr(USF)=0,0
Exp/Cntr=0.3,0.1

Type RM Length L Ch R = 1 ,128     ,115.3,128.1,139.4
XS GIS Cut Line= 3
2311940.86237565670464.9091807612311561.41813548 670406.52616971
2311438.59346633670540.438340058
#Sta/Elev= 30
       0 2483.72      29 2467.54    81.6 2441.66    93.8 2434.32   111.2 2425.51
   138.3 2407.39   158.5 2387.91   162.6 2384.62   166.6 2383.55   178.8 2382.71
   186.9 2377.57   190.9 2377.15     199 2377.25   211.1  2379.7   219.2 2377.19
   239.5 2377.54   259.9  2375.9   267.8 2375.32   275.9  2375.9     284 2380.49
   292.1 2381.92   305.5 2387.55   326.6 2391.06   337.1 2394.59   356.8 2404.04
   383.9 2418.68   440.5 2439.57   496.1 2462.25   545.5 2484.19   565.6 2491.95
#Mann= 5, -1 ,  0
       0     0.1       0      90    0.06       0   259.9   0.045       0
   275.9    0.06       0     290     0.1       0
#XS Ineff= 2 , 0
          211.98 2388.84
Permanent Ineff=
       F       F
Bank Sta=259.9,275.9
XS Rating Curve= 0 ,0
Exp/Cntr(USF)=0,0
Exp/Cntr=0.3,0.1

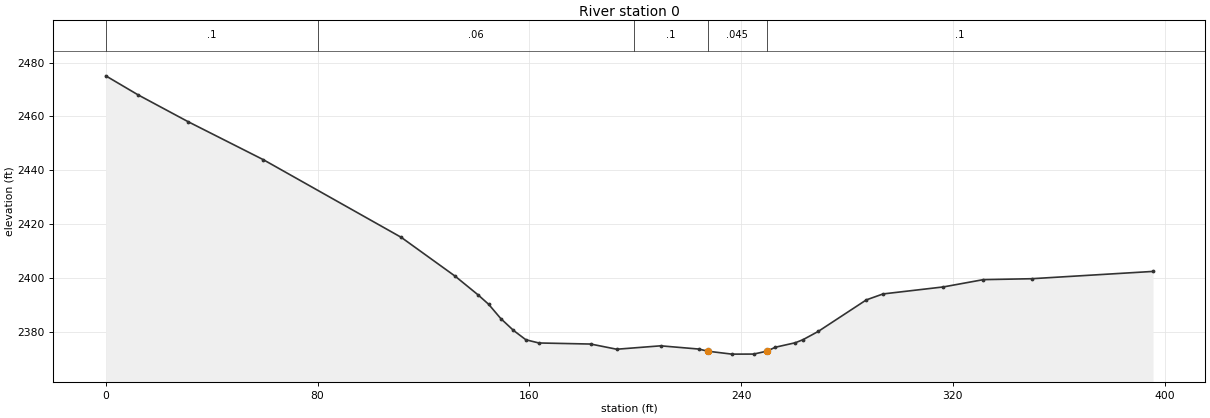
Type RM Length L Ch R = 1 ,0       ,31.9,35.3,38.6
XS GIS Cut Line= 5
 2311926.4929505670456.701425856 2311791.5228368670371.698584684
 2311741.3543004670336.2759348182311732.27389828670299.409402902
2311627.36462561670211.749385274
#Sta/Elev= 30
       0 2475.12    12.2 2468.04    31.1 2458.06    59.5 2443.93   111.6 2415.04
   131.9 2400.64   140.6 2393.66   144.6 2390.16   149.2 2384.83     154 2380.42
   158.7 2376.92   163.6 2375.74   183.2 2375.34     193 2373.41   209.6 2374.68
   224.1 2373.47  227.352372.684   236.5 2371.59   244.7 2371.61  249.742372.685
   252.9 2374.15   260.5 2375.83   263.4 2376.98   269.1 2380.02   287.3 2391.77
   293.6 2393.98   316.4 2396.59   331.5  2399.3   349.7 2399.64   395.6 2402.36
#Mann= 5, -1 ,  0
       0     0.1       0      80    0.06       0  199.51     0.1       0
  227.35   0.045       0  249.74     0.1       0
Bank Sta=227.35,249.74
XS Rating Curve= 0 ,0
Exp/Cntr=0.3,0.1
LCMann Table=0

Chan Stop Cuts=-1
Use User Specified Reach Order=0
Composite Channel Slope=5